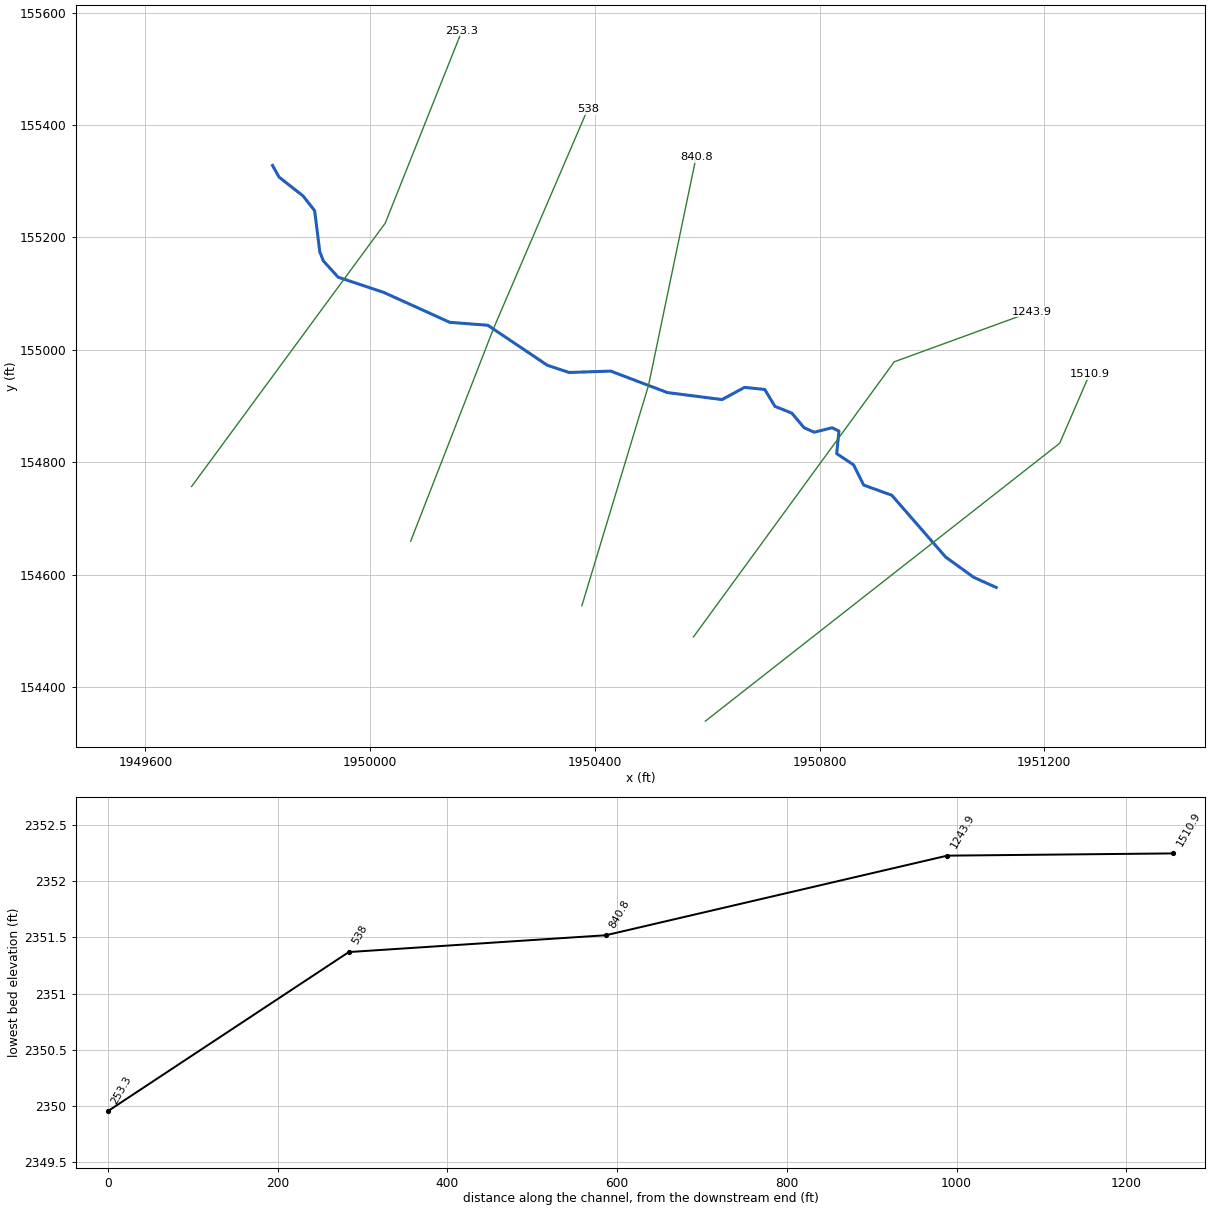
--- BvrBrnch.prj (project) ---

Proj Title=BvrBrnch
Current Plan=p01
Default Exp/Contr=0,0
English Units
Geom File=g01
Flow File=f01
Plan File=p01
BEGIN DESCRIPTION:
END DESCRIPTION:
DSS Export Rating Curves= 0
DSS Export Rating Curve Sorted= 0
DSS Export Volume Flow Curves= 0
DXF OffsetX= 0
DXF OffsetY= 0
DXF ScaleX= 0
DXF ScaleY= 0

--- BvrBrnch.p01 (plan) ---

Plan Title=Floodplain
Program Version=4.00
Geom File=g01
Flow File=f01
K Sum by GR=0
Std Step Tol=0.01
Critical Tol=0.01
Num of Std Step Trials=20
Max Error Tol=0.3
Flow Tol Ratio=0.001
Split Flow NTrial=30
Split Flow Tol=0.02
Split Flow Ratio=0.02
Log Output Level=0
Friction Slope Method=1
Unsteady Friction Slope Method=2
Unsteady Bridges Friction Slope Method=1
Global Log Level=0
CheckData=False
Run HTab=0
Run UNet=0
Run PostProcess=0
UNET Theta=0
UNET Theta Warmup=0
UNET ZTol=0
UNET ZSATol=0
UNET MxIter=0
UNET MaxInSteps=0
UNET DtIC=0
UNET DtMin=0
UNET MaxCRTS=0
UNET WFStab=0
UNET SFStab=0
UNET WFX=0
UNET SFX=0
UNET DSS MLevel=0
UNET DZMax Abort=0
UNET Convert EG Bridges=0
UNET Use Existing IB Tables=0
UNET Froude Limit=0
UNET Froude Power=0
Write IC File=0
Echo Input=False
Echo Output=False
Write Detailed=0

--- BvrBrnch.f01 (steady flow) ---

Flow Title=NFF Regression Equation
Program Version=4.00
Number of Profiles=1
Profile Names=P100yr
River Rch & RM=BvrBrnch,Main      ,1510.9
545.8678
River Rch & RM=BvrBrnch,Main      ,253.3
556.0473
Boundary for River Rch & Prof#=BvrBrnch,Main      ,1
Up Type=0
Dn Type=3
Dn Slope=0.006273

--- BvrBrnch.g01 (geometry) ---

Geom Title=USGS 3m DEM
Program Version=4.00

River Reach=BvrBrnch     ,Main
Reach XY= 30
     1951114.399      154577.078     1951074.393      154595.116
     1951024.409      154631.173     1950928.434      154741.276
     1950878.419      154759.297     1950860.438      154795.357
     1950830.423      154815.356     1950834.457      154855.383
     1950822.438      154861.387     1950790.450      154853.397
     1950772.431      154861.420     1950750.436      154887.433
     1950720.436      154899.469     1950702.450      154929.485
     1950666.376      154933.212     1950626.392      154911.523
     1950528.927      154923.993     1950428.233      154962.187
     1950354.338      154959.722     1950315.385      154972.604
     1950209.483      155043.784     1950141.774      155048.993
     1950024.196      155102.272     1949943.075      155129.365
     1949916.794      155158.274     1949910.457      155174.568
     1949901.278      155247.751     1949880.723      155273.837
     1949838.142      155307.294     1949826.335      155328.219

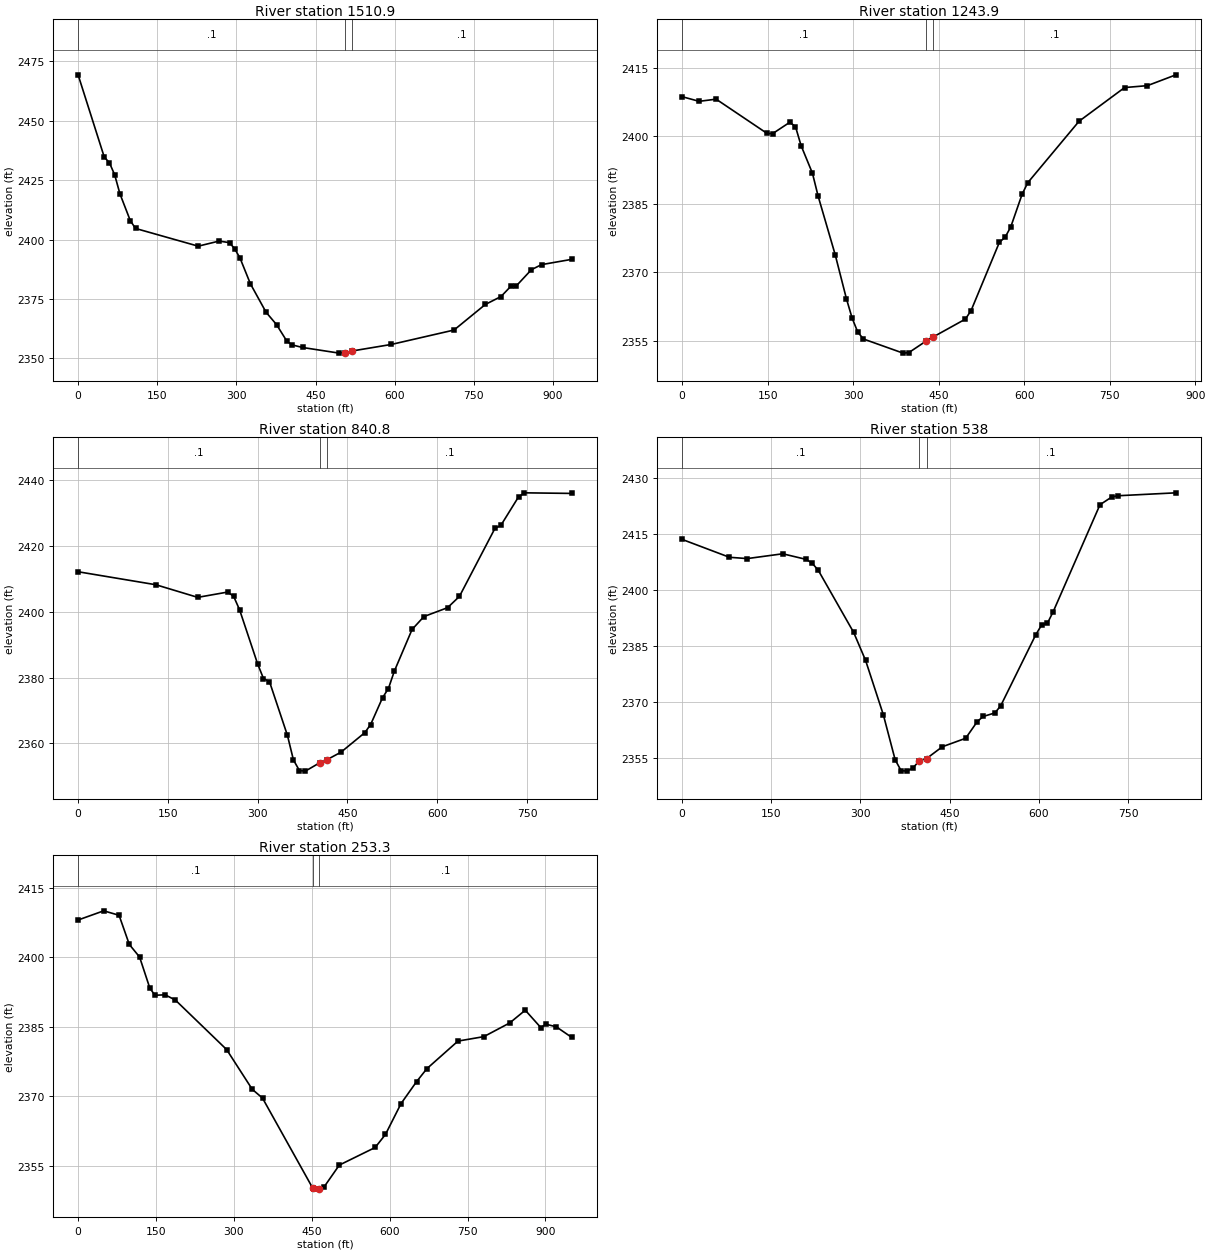
Type RM Length L Ch R = 1 ,1510.9,251.1,266.5,282.2
XS GIS Cut Line= 3
     1950596.689      154339.180     1951227.292      154833.735
     1951280.608      154956.914
#Sta/Elev= 30
       0 2469.21    49.5 2434.69    59.4 2432.22    69.3 2427.19    79.2 2419.24
    98.9 2407.93   108.8 2404.65   227.6 2397.20   267.1 2399.34   286.9 2398.68
   296.8 2396.05   306.7 2392.27   326.5 2381.38   356.2 2369.43   376.0 2364.24
   395.8 2357.20   405.6 2355.70   425.4 2354.62   494.7 2352.25   506.6 2352.46
   518.6 2353.13   593.6 2355.90   712.4 2361.96   771.7 2372.71   801.4 2376.04
   820.6 2380.48   830.2 2380.47   858.9 2387.30   878.1 2389.44   935.6 2391.67
#Mann= 3 , 0 , 0
       0     0.1       0   506.6   0.045       0   518.6     0.1       0
Bank Sta=   506.6,   518.6
Exp/Cntr=0.3,0.1

Type RM Length L Ch R = 1 ,1243.9,390.7,402.2,402.4
XS GIS Cut Line= 3
     1950575.467      154489.036     1950932.903      154978.746
     1951177.146      155067.756
#Sta/Elev= 30
       0 2408.63    29.8 2407.61    59.6 2408.09   149.1 2400.54   159.0 2400.53
   188.8 2403.00   198.8 2402.06   208.7 2397.86   228.6 2391.79   238.5 2386.78
   268.4 2373.92   288.2 2364.19   298.2 2359.93   308.1 2356.85   318.0 2355.34
   387.6 2352.23   397.6 2352.34   428.3 2354.91   440.3 2355.78   497.0 2359.72
   506.9 2361.60   556.6 2376.62   566.5 2377.70   576.5 2379.99   596.3 2387.14
   606.3 2389.71   696.3 2403.23   776.2 2410.64   816.2 2411.06   866.2 2413.44
#Mann= 3 , 0 , 0
       0     0.1       0   428.3   0.045       0   440.3     0.1       0
Bank Sta=   428.3,   440.3
Exp/Cntr=0.3,0.1

Type RM Length L Ch R = 1 ,840.8,304.5,302.9,298.7
XS GIS Cut Line= 3
     1950376.898      154544.592     1950495.529      154936.661
     1950580.230      155343.110
#Sta/Elev= 30
       0 2412.17   129.9 2408.22   199.8 2404.38   249.8 2405.99   259.8 2404.70
   269.8 2400.58   299.7 2384.24   309.7 2379.67   319.7 2378.75   349.7 2362.38
   359.7 2354.93   369.7 2351.69   379.6 2351.52   403.6 2354.06   415.6 2354.98
   439.3 2357.30   478.8 2363.20   488.7 2365.70   508.5 2373.83   518.4 2376.65
   528.2 2381.90   557.9 2394.62   577.7 2398.54   617.2 2401.24   637.0 2404.67
   696.3 2425.35   706.2 2426.27   735.8 2434.96   745.7 2436.18   824.8 2436.00
#Mann= 3 , 0 , 0
       0     0.1       0   403.6   0.045       0   415.6     0.1       0
Bank Sta=   403.6,   415.6
Exp/Cntr=0.3,0.1

Type RM Length L Ch R = 1 ,538,289.8,284,279
XS GIS Cut Line= 3
     1950072.242      154659.520     1950220.406      155039.768
     1950387.181      155428.009
#Sta/Elev= 30
       0 2413.60    79.6 2408.80   109.5 2408.45   169.2 2409.74   209.0 2408.22
   219.0 2407.16   228.9 2405.33   288.6 2388.60   308.6 2381.10   338.4 2366.53
   358.3 2354.43   368.3 2351.50   378.2 2351.37   388.2 2352.22   399.2 2354.18
   411.2 2354.75   437.6 2357.91   476.9 2360.19   496.5 2364.68   506.4 2366.05
   526.0 2366.99   535.8 2368.89   594.8 2387.98   604.6 2390.59   614.4 2391.07
   624.3 2394.23   702.9 2422.92   722.6 2424.98   732.4 2425.32   830.6 2426.11
#Mann= 3 , 0 , 0
       0     0.1       0   399.2   0.045       0   411.2     0.1       0
Bank Sta=   399.2,   411.2
Exp/Cntr=0.3,0.1

Type RM Length L Ch R = 1 ,253.3,262,253,243.9
XS GIS Cut Line= 3
     1949682.268      154756.748     1950026.985      155225.564
     1950163.604      155568.253
#Sta/Elev= 30
       0 2408.07    49.3 2410.05    78.9 2409.09    98.6 2402.79   118.4 2400.07
   138.1 2393.37   147.9 2391.82   167.7 2391.91   187.4 2390.77   286.0 2380.09
   335.3 2371.51   355.1 2369.61   451.4 2350.25   453.7 2349.95   463.4 2349.96
   473.4 2350.38   503.0 2355.14   572.0 2358.94   591.9 2361.76   621.8 2368.41
   651.7 2373.15   671.6 2375.96   731.5 2381.92   781.3 2382.88   831.2 2385.84
   861.1 2388.59   891.0 2384.84   901.0 2385.56   920.9 2385.00   950.8 2382.70
#Mann= 3 , 0 , 0
       0     0.1       0   451.4   0.045       0   463.4     0.1       0
Bank Sta=   451.4,   463.4
Exp/Cntr=0.3,0.1